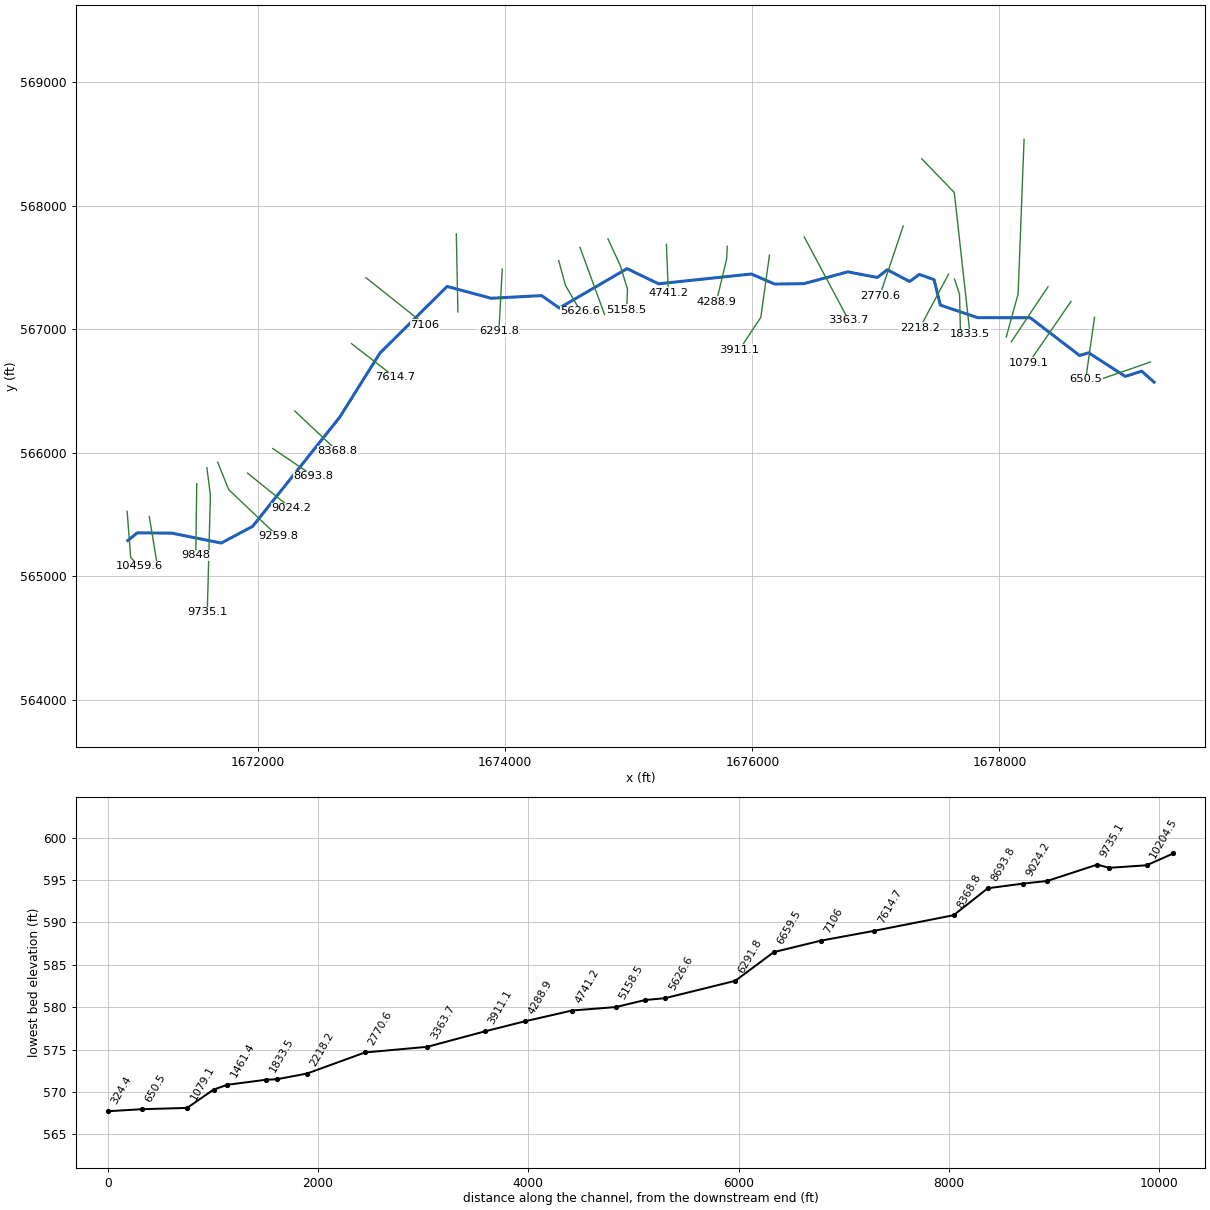
--- NP7.prj (project) ---

Proj Title=NP7
Current Plan=p01
Default Exp/Contr=0,0
English Units
Geom File=g01
Flow File=f01
Plan File=p01
BEGIN DESCRIPTION:
AMEC Environment & Infrastructure, 2013
Projection: NAD 1983 State Plane West Virginia South FIPS 4702 (US Feet)
Vertical Datum: NAVD 1988
END DESCRIPTION:
DSS Export Rating Curves= 0
DSS Export Rating Curve Sorted= 0
DSS Export Volume Flow Curves= 0
DXF OffsetX= 0
DXF OffsetY= 0
DXF ScaleX= 0
DXF ScaleY= 0

--- NP7.p01 (plan) ---

Plan Title=Floodplain
Program Version=4.00
Geom File=g01
Flow File=f01
K Sum by GR=0
Std Step Tol=0.01
Critical Tol=0.01
Num of Std Step Trials=20
Max Error Tol=0.3
Flow Tol Ratio=0.001
Split Flow NTrial=30
Split Flow Tol=0.02
Split Flow Ratio=0.02
Log Output Level=0
Friction Slope Method=1
Unsteady Friction Slope Method=2
Unsteady Bridges Friction Slope Method=1
Global Log Level=0
CheckData=False
Run HTab=0
Run UNet=0
Run PostProcess=0
UNET Theta=0
UNET Theta Warmup=0
UNET ZTol=0
UNET ZSATol=0
UNET MxIter=0
UNET MaxInSteps=0
UNET DtIC=0
UNET DtMin=0
UNET MaxCRTS=0
UNET WFStab=0
UNET SFStab=0
UNET WFX=0
UNET SFX=0
UNET DSS MLevel=0
UNET DZMax Abort=0
UNET Convert EG Bridges=0
UNET Use Existing IB Tables=0
UNET Froude Limit=0
UNET Froude Power=0
Write IC File=0
Echo Input=False
Echo Output=False
Write Detailed=0

--- NP7.f01 (steady flow) ---

Flow Title=USGS Regress. Eqn. (2010) - Western-Plateaus
Program Version=4.10
Number of Profiles= 1
Profile Names=P100yr
River Rch & RM=NP7,Main            ,10459.6
    1040
River Rch & RM=NP7,Main            ,9259.8
    1050
River Rch & RM=NP7,Main            ,8368.8
    1151
River Rch & RM=NP7,Main            ,6659.5
    1169
River Rch & RM=NP7,Main            ,5626.6
    1303
River Rch & RM=NP7,Main            ,3911.1
    1342
River Rch & RM=NP7,Main            ,1833.5
    1376
River Rch & RM=NP7,Main            ,1461.4
    1831
Boundary for River Rch & Prof#=NP7,Main            , 1
Up Type= 0
Dn Type= 3
Dn Slope=0.0005
DSS Import GetInterval= 0
DSS Import GetPeak= 0
DSS Import FillOption= 0

--- NP7.g01 (geometry) ---

Geom Title=USGS 3m DEM
Program Version=4.10

River Reach=NP7             ,Main
Reach XY= 30
     1670945.384      565288.159     1671022.253      565350.344
     1671302.201      565348.174     1671701.507      565267.879
     1671955.413      565402.428     1672661.793      566287.844
     1672986.229      566805.422     1673529.849      567344.702
     1673886.837      567249.216     1674294.823      567270.917
     1674438.052      567170.006     1674986.012      567489.016
     1675241.003      567366.403     1675992.957      567445.613
     1676180.674      567364.233     1676417.219      567367.488
     1676773.121      567462.974     1677011.837      567417.402
     1677092.132      567480.336     1677273.338      567384.849
     1677351.463      567442.358     1677470.821       567400.04
     1677521.819      567193.877     1677824.554      567091.881
     1678249.402      567091.707     1678648.707      566786.152
     1678722.319      566807.679     1679018.416      566616.775
     1679151.485      566659.068     1679251.524       566570.39

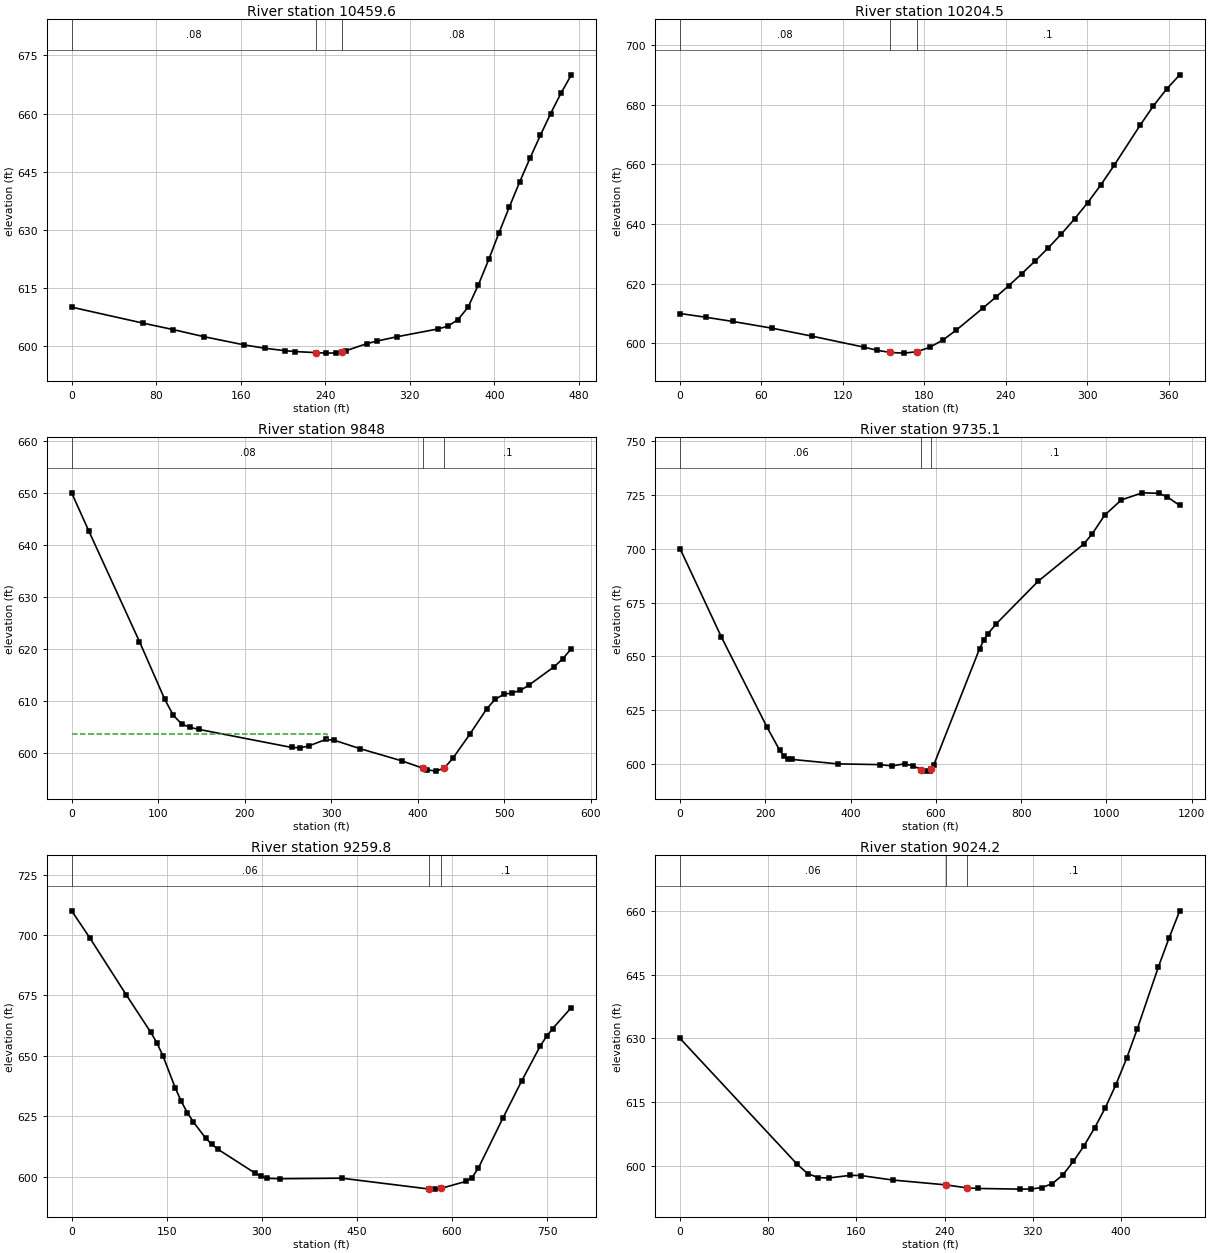
Type RM Length L Ch R = 1 ,10459.6 ,257.5,255.2,255.8
XS GIS Cut Line= 3
     1670940.395      565524.157     1670969.342      565150.142
     1671038.496      565081.245
#Sta/Elev= 30
       0     610    67.3  605.89    96.2   604.2     125  602.39   163.5  600.24
   182.8  599.39     202  598.76   211.6  598.53   230.8  598.27   240.5  598.13
   250.1  598.17   256.2  598.55   259.7  598.77     279  600.55   288.6  601.23
   307.8  602.36   346.3  604.36   355.9  605.08   365.5  606.77   375.1     610
   384.9   615.8   394.7  622.35   404.4  629.24   414.2  635.92   423.9  642.33
   433.7  648.49   443.5  654.37   453.2     660     463  665.26   472.8     670
#Mann= 3 , 0 , 0
       0     .08       0   230.8    .045       0   256.2     .08       0
Bank Sta=230.8,256.2
XS Rating Curve= 0 ,0
Exp/Cntr=0.3,0.1

Type RM Length L Ch R = 1 ,10204.5 ,360,356.5,352.1
XS GIS Cut Line= 2
     1671119.701      565482.514     1671179.611      565119.197
#Sta/Elev= 28
       0     610    19.4  608.73    38.8  607.35    67.8  605.09    96.9  602.45
   135.7  598.71   145.4  597.67     155  596.95   164.7  596.73   174.4  597.18
   184.1   598.7   193.8  601.17   203.5  604.43   222.9  611.72   232.6  615.46
   242.2  619.35   251.9   623.4   261.6   627.6   271.3  632.01     281  636.69
   290.7  641.71   300.4  647.18   310.1  653.15   319.8  659.63   339.2  673.26
   348.8  679.61   358.5  685.24   368.2  690.02
#Mann= 3 , 0 , 0
       0     .08       0     155    .045       0   174.4      .1       0
Bank Sta=155,174.4
XS Rating Curve= 0 ,0
Exp/Cntr=0.3,0.1

Type RM Length L Ch R = 1 ,9848    ,112.7,112.9,112.2
XS GIS Cut Line= 2
      1671503.67      565748.374     1671495.989      565170.611
#Sta/Elev= 30
       0     650    19.6  642.74    78.4  621.37   107.7  610.24   117.5  607.19
   127.3  605.49   137.1  604.85   146.9  604.47   254.6  600.98   264.4  600.93
   274.2  601.28   293.8  602.52   303.6  602.38     333  600.78   381.9   598.4
   406.5  596.97   411.3  596.68   421.1  596.43   430.9  597.02   440.7  598.89
   460.3   603.5   479.9  608.41   489.7  610.25   499.5   611.2   509.3   611.5
     519  611.98   528.8  612.99   558.2  616.56     568  618.08   577.8     620
#Mann= 3 , 0 , 0
       0     .08       0   406.5    .045       0   430.9      .1       0
#XS Ineff= 2 , 0
          294.93  603.61
Permanent Ineff=
       F       F
Bank Sta=406.5,430.9
XS Rating Curve= 0 ,0
Exp/Cntr=0.3,0.1

Type RM Length L Ch R = 1 ,9735.1  ,455.8,475.3,494.9
XS GIS Cut Line= 3
     1671585.967      565877.091     1671614.249      565655.359
     1671588.929       564707.23
#Sta/Elev= 30
       0     700    97.2  658.89   204.1  617.16   233.3  606.62   243.1  603.96
   252.9  602.66   262.6  602.24   370.2  600.17     468  599.83   497.3  599.22
   526.6  600.21   546.2  599.27   565.8  597.56   575.5  596.81   585.3  597.08
   587.5  597.67   595.1  599.69   702.6  653.61   712.4   657.5   722.2  660.51
   741.8  665.16   839.5  684.78   947.1  702.17   966.7  706.81     996  715.54
  1035.1  722.56    1084  725.86  1123.1  725.63  1142.7  723.98    1172     720
#Mann= 3 , 0 , 0
       0     .06       0   565.8    .045       0   587.5      .1       0
Bank Sta=565.8,587.5
XS Rating Curve= 0 ,0
Exp/Cntr=0.3,0.1

Type RM Length L Ch R = 1 ,9259.8  ,234.4,235.6,235.7
XS GIS Cut Line= 3
     1671673.154      565922.577     1671762.675      565699.727
     1672160.375      565322.403
#Sta/Elev= 30
       0     710    28.8  698.74    86.5   675.1   124.9  659.72   134.5  655.39
   144.1  649.98   163.3  636.88   172.9  631.18   182.5  626.55   192.1  622.64
   211.3  616.01     221  613.48   230.6   611.4   289.1  601.55   298.9  600.16
   308.7  599.37   328.3  599.18   426.2   599.4   563.2  594.95     573  594.88
   582.4  595.17     622  598.07   631.7  599.66   641.5  603.48   680.7  624.41
   710.1  639.66   739.4  654.11   749.2  658.03     759   661.3   788.4     670
#Mann= 3 , 0 , 0
       0     .06       0   563.2    .045       0   582.4      .1       0
Bank Sta=563.2,582.4
XS Rating Curve= 0 ,0
Exp/Cntr=0.3,0.1

Type RM Length L Ch R = 1 ,9024.2  ,327.9,330.4,333.7
XS GIS Cut Line= 2
     1671914.497      565833.994     1672267.691      565549.698
#Sta/Elev= 26
       0     630   106.1  600.46   115.8  598.21   125.4  597.27     135  597.18
   154.4   597.8     164  597.76   192.9   596.7   240.9  595.57   260.5  594.85
   270.1  594.72   308.7  594.56   318.3  594.58     328  594.91   337.6  595.82
   347.3  597.89   356.9  601.08   366.6  604.76   376.2  608.97   385.9  613.71
   395.5  619.14   405.2  625.31   414.8  632.19   434.1  646.87   443.8  653.68
   453.4  660.01
#Mann= 3 , 0 , 0
       0     .06       0   240.9    .045       0   260.5      .1       0
Bank Sta=240.9,260.5
XS Rating Curve= 0 ,0
Exp/Cntr=0.3,0.1

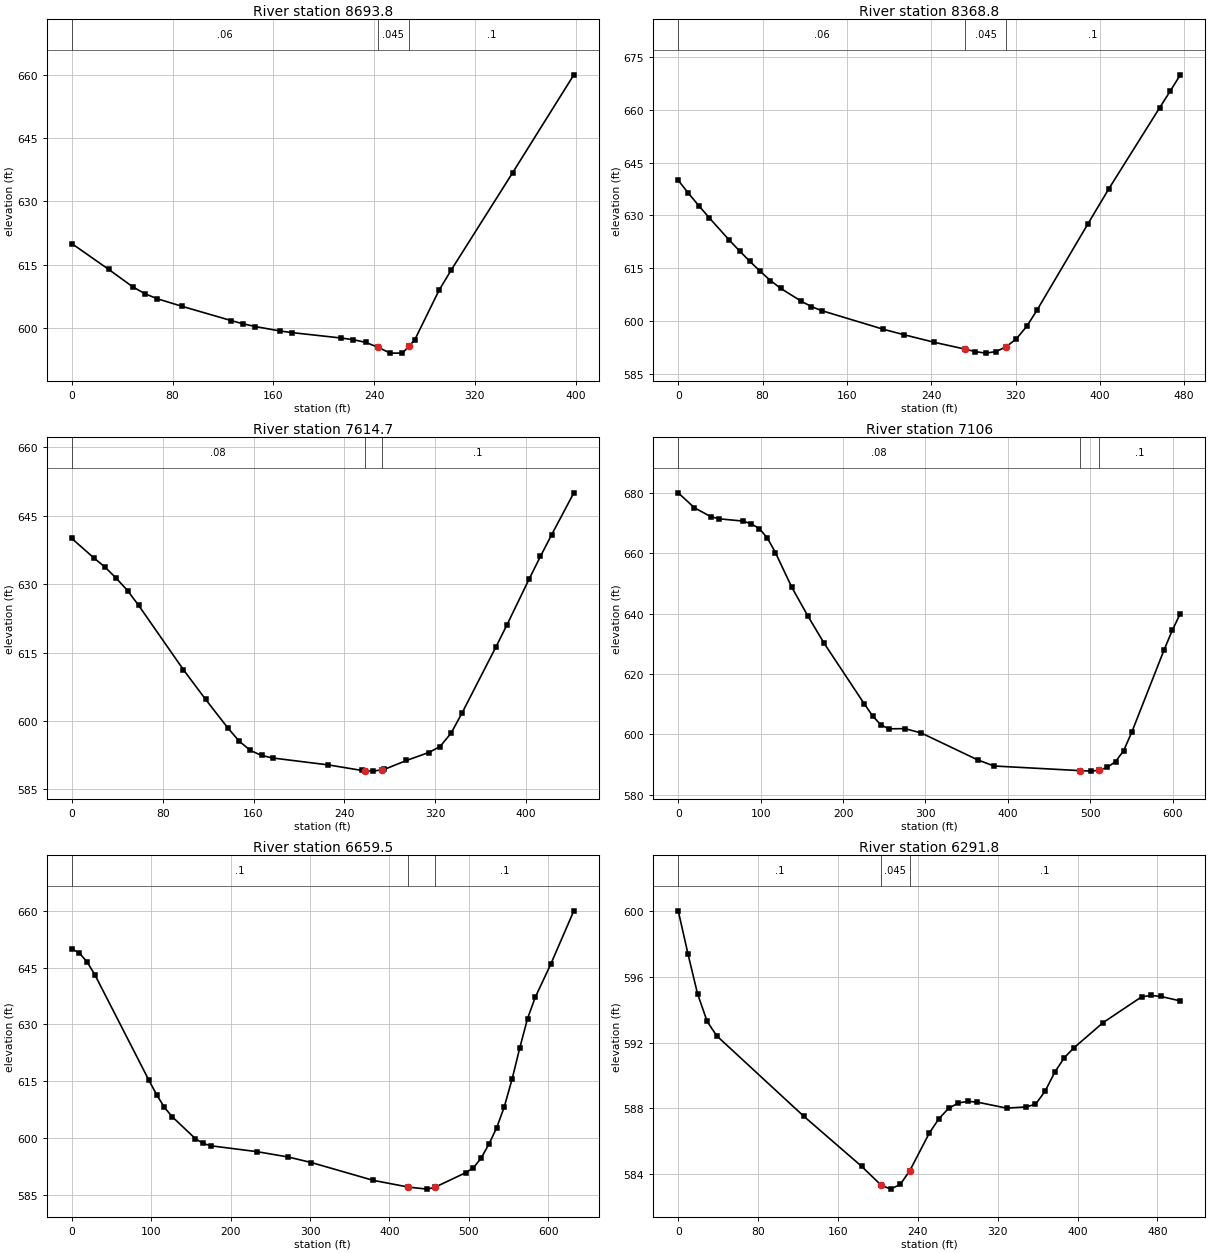
Type RM Length L Ch R = 1 ,8693.8  ,326.5,325,323.3
XS GIS Cut Line= 2
     1672119.128      566032.906     1672449.283       565809.59
#Sta/Elev= 23
       0     620    29.2  613.89    48.6   609.7    58.3  608.07      68   606.9
    87.5  605.12   126.4  601.75   136.1  600.96   145.8  600.32   165.3  599.27
     175  598.88   213.9   597.6   223.6   597.2   233.3  596.57     243  595.43
   252.7  594.03   262.5  594.02   267.7  595.68   272.2  597.12   291.6  608.93
   301.4   613.8     350  636.79   398.6     660
#Mann= 3 , 0 , 0
       0     .06       0     243    .045       0   267.7      .1       0
Bank Sta=243,267.7
XS Rating Curve= 0 ,0
Exp/Cntr=0.3,0.1

Type RM Length L Ch R = 1 ,8368.8  ,754.4,754.2,753.8
XS GIS Cut Line= 2
     1672297.377      566336.939     1672643.863      566010.137
#Sta/Elev= 29
       0     640     9.7   636.3    19.4  632.82    29.2  629.41    48.6  622.92
    58.3  619.87      68  616.93    77.8   614.1    87.5  611.48    97.2  609.26
   116.6  605.62   126.4  604.07   136.1  602.93   194.4  597.64   213.8   596.1
     243  593.91   272.2  591.97   281.9  591.27   291.6  590.84   301.3  591.27
     311  592.63   320.8  594.91   330.5  598.42   340.2  602.98   388.8  627.69
   408.2  637.44   456.8  660.69   466.6  665.31   476.3     670
#Mann= 3 , 0 , 0
       0     .06       0   272.2    .045       0     311      .1       0
Bank Sta=272.2,311
XS Rating Curve= 0 ,0
Exp/Cntr=0.3,0.1

Type RM Length L Ch R = 1 ,7614.7  ,507.8,508.7,508.3
XS GIS Cut Line= 2
     1672756.503      566881.748     1673105.867      566611.124
#Sta/Elev= 30
       0     640    19.6   635.7    29.5  633.66    39.3  631.24    49.1  628.57
    58.9  625.31    98.2  611.25   117.8  604.72   137.5  598.42   147.3  595.58
   157.1  593.55     167  592.44   176.8  591.88   225.9  590.36   255.3  589.15
   257.8  589.11   265.2     589   272.8  589.29     275  589.37   294.6  591.34
   314.2  593.08   324.1  594.38   333.9  597.34   343.7  601.84   373.2  616.16
     383  621.04   402.6  631.13   412.5  636.07   422.3  640.79   441.9     650
#Mann= 3 , 0 , 0
       0     .08       0   257.8    .045       0   272.8      .1       0
Bank Sta=257.8,272.8
XS Rating Curve= 0 ,0
Exp/Cntr=0.3,0.1

Type RM Length L Ch R = 1 ,7106    ,466.1,446.5,426.9
XS GIS Cut Line= 2
     1672873.939      567415.243     1673350.523      567035.758
#Sta/Elev= 30
       0     680    19.6  675.06    39.3  672.14    49.1  671.41    78.6  670.64
    88.4  669.76    98.3  668.18   108.1  665.06   117.9  660.23   137.6  648.82
   157.2  639.25   176.9  630.23     226  610.01   235.8  606.16   245.6   603.2
   255.5  601.85   275.1  601.91   294.8  600.48   363.6  591.53   383.2  589.54
   487.2  588.01   501.1  587.84     511  588.14   520.8  589.12   530.6     591
   540.4  594.59   550.3  600.73   589.6  628.05   599.4  634.43   609.2  640.02
#Mann= 3 , 0 , 0
       0     .08       0   487.2    .045       0     511      .1       0
Bank Sta=487.2,511
XS Rating Curve= 0 ,0
Exp/Cntr=0.3,0.1

Type RM Length L Ch R = 1 ,6659.5  ,369.5,367.7,365.6
XS GIS Cut Line= 2
     1673604.368      567770.331     1673617.499      567138.327
#Sta/Elev= 30
       0     650     9.7  648.81    19.4  646.47    29.2  643.06    97.2  615.21
     107  611.36   116.7  608.07   126.4  605.62   155.6  599.82   165.3  598.57
     175  597.94   233.4  596.38   272.3  594.98   301.5  593.52   379.3  588.82
   423.8  587.03   447.4  586.49   457.1  586.97     496  590.84   505.7  592.13
   515.4  594.69   525.2  598.38   534.9  602.67   544.6  608.28   554.3  615.51
   564.1  623.85   573.8  631.54   583.5  637.15     603   645.9   632.1     660
#Mann= 3 , 0 , 0
       0      .1       0   423.8    .045       0   457.1      .1       0
Bank Sta=423.8,457.1
XS Rating Curve= 0 ,0
Exp/Cntr=0.3,0.1

Type RM Length L Ch R = 1 ,6291.8  ,650.5,665.2,679.5
XS GIS Cut Line= 2
     1673976.299       567485.06     1673949.264      566982.832
#Sta/Elev= 29
       0     600     9.7   597.4    19.3  594.97      29  593.28    38.7   592.4
   125.7  587.53   183.8  584.48   203.1  583.35   212.8   583.1   222.5  583.39
   232.1  584.23   251.5   586.5   261.2  587.38   270.8     588   280.5  588.33
   290.2  588.43   299.8  588.38   328.9  588.02   348.2  588.09   357.9  588.25
   367.5  589.04   377.2   590.2   386.9  591.09   396.6  591.69   425.6  593.21
   464.3  594.78   473.9  594.86   483.6   594.8     503  594.53
#Mann= 3 , 0 , 0
       0      .1       0   203.1    .045       0   232.1      .1       0
Bank Sta=203.1,232.1
XS Rating Curve= 0 ,0
Exp/Cntr=0.3,0.1

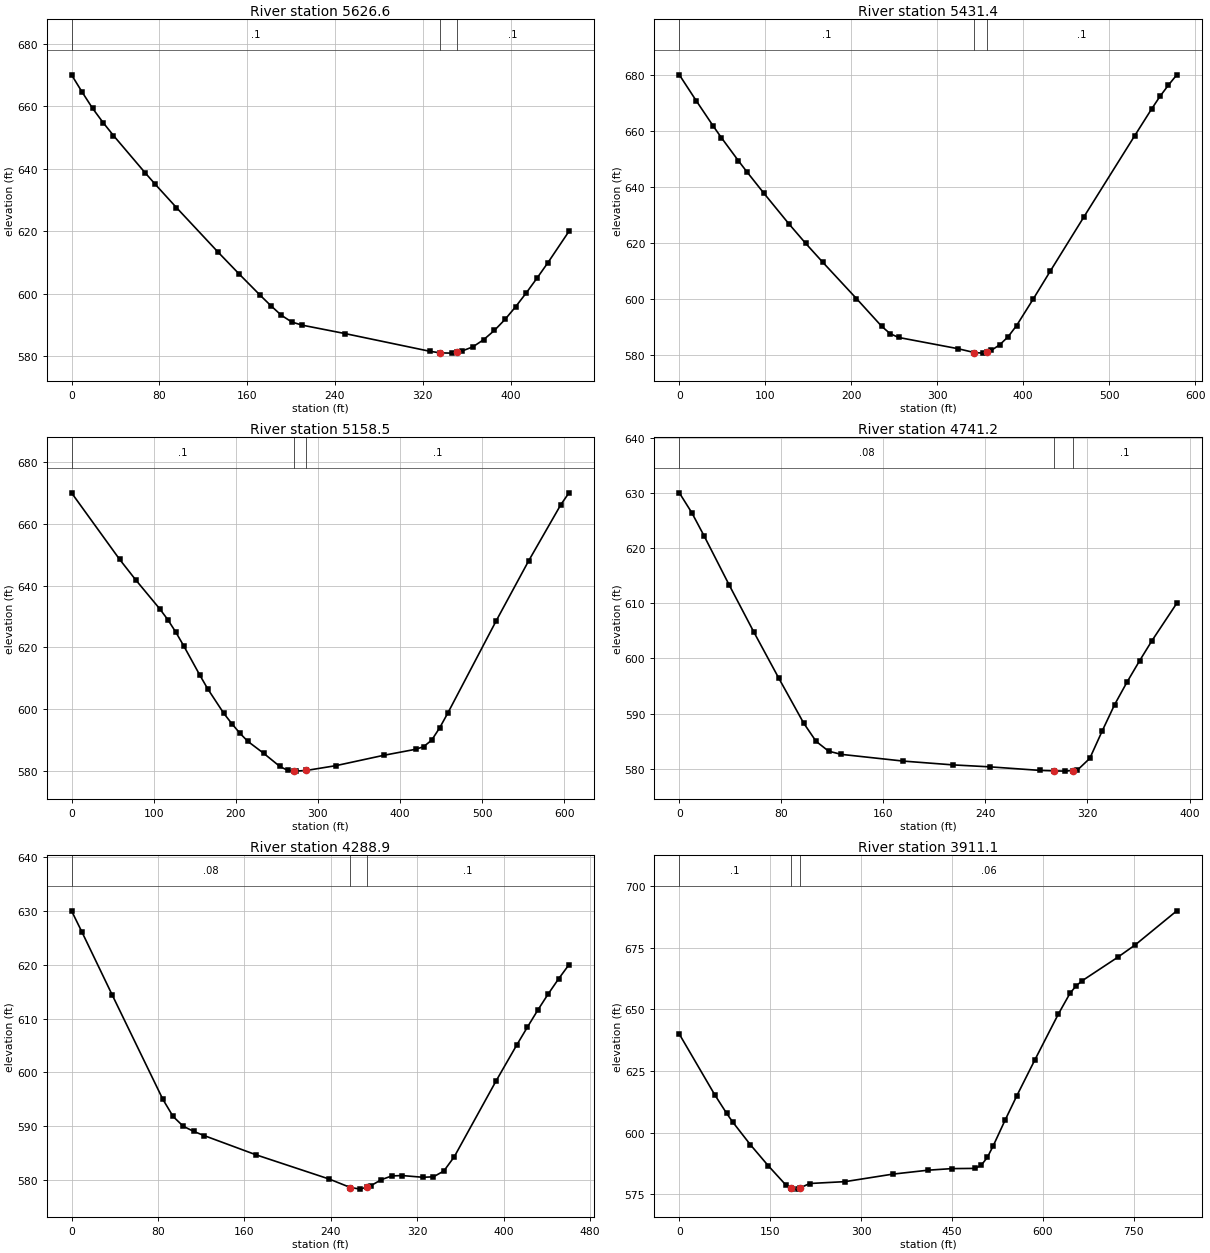
Type RM Length L Ch R = 1 ,5626.6  ,199.2,195.2,191.3
XS GIS Cut Line= 3
      1674432.64      567555.298     1674488.109      567352.609
     1674610.385      567142.493
#Sta/Elev= 30
       0     670     9.6  664.51    19.1  659.33    28.7  654.76    38.2   650.6
    66.9  638.75    76.4  634.96    95.5   627.6   133.7  613.26   152.8  606.31
   171.9  599.54   181.5  596.25     191   593.2   200.6  591.01   210.1     590
     249  587.32   326.8  581.62   336.1  581.14   346.3  581.06   351.1  581.41
     356  581.77   365.7  583.08   375.4  585.35   385.2   588.3   394.9  591.82
   404.6  595.89   414.4  600.37   424.1  605.05   433.8  609.87   453.2     620
#Mann= 3 , 0 , 0
       0      .1       0   336.1    .045       0   351.1      .1       0
Bank Sta=336.1,351.1
XS Rating Curve= 0 ,0
Exp/Cntr=0.3,0.1

Type RM Length L Ch R = 1 ,5431.4  ,272.8,272.9,272.8
XS GIS Cut Line= 2
     1674605.532      567660.667     1674804.463      567117.248
#Sta/Elev= 30
       0     680    19.6   670.8    39.2  661.85      49  657.57    68.7  649.39
    78.5  645.48    98.1  637.91   127.5  626.88   147.1   619.9   166.7  613.27
     206  600.29   235.4  590.39   245.2  587.78     255  586.42   323.7  582.44
   343.3  581.03   353.1  580.83   358.3  581.34   362.9   581.8   372.7   583.8
   382.5  586.67   392.3  590.63     412  600.25   431.6  610.08   470.8  629.45
   529.6  658.23   549.3  667.77   559.1   672.3   568.9   676.3   578.7     680
#Mann= 3 , 0 , 0
       0      .1       0   343.3    .045       0   358.3      .1       0
Bank Sta=343.3,358.3
XS Rating Curve= 0 ,0
Exp/Cntr=0.3,0.1

Type RM Length L Ch R = 1 ,5158.5  ,422.8,417.3,410.9
XS GIS Cut Line= 4
     1674831.572      567729.901     1674930.286      567517.612
     1674990.076      567322.295     1674983.101      567155.145
#Sta/Elev= 30
       0     670    58.5   648.5      78   641.9   107.3  632.52   117.1  629.03
   126.8  625.02   136.6  620.52   156.1   611.1   165.8  606.62   185.3  598.73
   195.1  595.38   204.8  592.32   214.6  589.65   234.1  585.74   253.6  581.53
   263.3  580.24   270.9  580.06     273  580.01   285.9  580.23   321.7  581.77
     380  585.12   418.9  587.07   428.6   587.9   438.4     590   448.2  593.99
   458.1  598.77   517.1  628.64   556.5  647.98   595.8   666.2   605.7  670.01
#Mann= 3 , 0 , 0
       0      .1       0   270.9    .045       0   285.9      .1       0
Bank Sta=270.9,285.9
XS Rating Curve= 0 ,0
Exp/Cntr=0.3,0.1

Type RM Length L Ch R = 1 ,4741.2  ,458.7,452.3,446.3
XS GIS Cut Line= 2
     1675305.036      567685.511     1675320.623      567295.807
#Sta/Elev= 25
       0     630     9.8  626.39    19.5  622.17      39  613.35    58.5  604.75
      78  596.42    97.5  588.29   107.2     585     117  583.22   126.8  582.64
   175.5  581.42   214.5  580.73   243.8  580.37   282.8  579.73   293.4  579.65
   302.3   579.6   308.4  579.71     312  579.77   321.8  581.91   331.5  586.86
   341.3  591.66     351  595.73   360.8  599.57   370.5  603.21     390     610
#Mann= 3 , 0 , 0
       0     .08       0   293.4    .045       0   308.4      .1       0
Bank Sta=293.4,308.4
XS Rating Curve= 0 ,0
Exp/Cntr=0.3,0.1

Type RM Length L Ch R = 1 ,4288.9  ,375,377.8,380.3
XS GIS Cut Line= 3
     1675797.433      567669.551     1675792.013      567566.249
     1675708.579      567219.028
#Sta/Elev= 28
       0     630     9.4  626.16    37.6   614.4    84.6  594.98      94  591.82
   103.4     590   113.1  589.04   122.8  588.26     171  584.68   238.6  580.19
   258.2  578.62   267.5  578.32   273.2   578.7   277.2  578.96   286.8  580.07
   296.5  580.77   306.1  580.84   325.4  580.52   335.1  580.61   344.7  581.68
   354.4  584.34     393  598.38   412.3  605.11   421.9  608.34   431.6  611.53
   441.2  614.52   450.9  617.35   460.6     620
#Mann= 3 , 0 , 0
       0     .08       0   258.2    .045       0   273.2      .1       0
Bank Sta=258.2,273.2
XS Rating Curve= 0 ,0
Exp/Cntr=0.3,0.1

Type RM Length L Ch R = 1 ,3911.1  ,523.8,547.4,563.8
XS GIS Cut Line= 3
     1676138.934       567598.21     1676068.787      567094.993
     1675896.525      566834.148
#Sta/Elev= 30
       0     640    58.6  615.34    78.2  607.83    87.9  604.41   117.2  595.16
   146.6  586.66   175.9  578.78   183.9  577.43   185.6  577.14   195.4  577.14
   198.9  577.59     215  579.42   273.6  580.18   351.8  583.21   410.4  584.82
   449.5  585.46   488.5  585.55   498.3   586.9   508.1  589.98   517.8  594.67
   537.4  605.08   556.9  615.05   586.2  629.38   625.3  648.13   644.8  656.67
   654.6  659.54   664.4  661.61     723  671.12   752.3  676.22   820.7     690
#Mann= 3 , 0 , 0
       0      .1       0   183.9    .045       0   198.9     .06       0
Bank Sta=183.9,198.9
XS Rating Curve= 0 ,0
Exp/Cntr=0.3,0.1

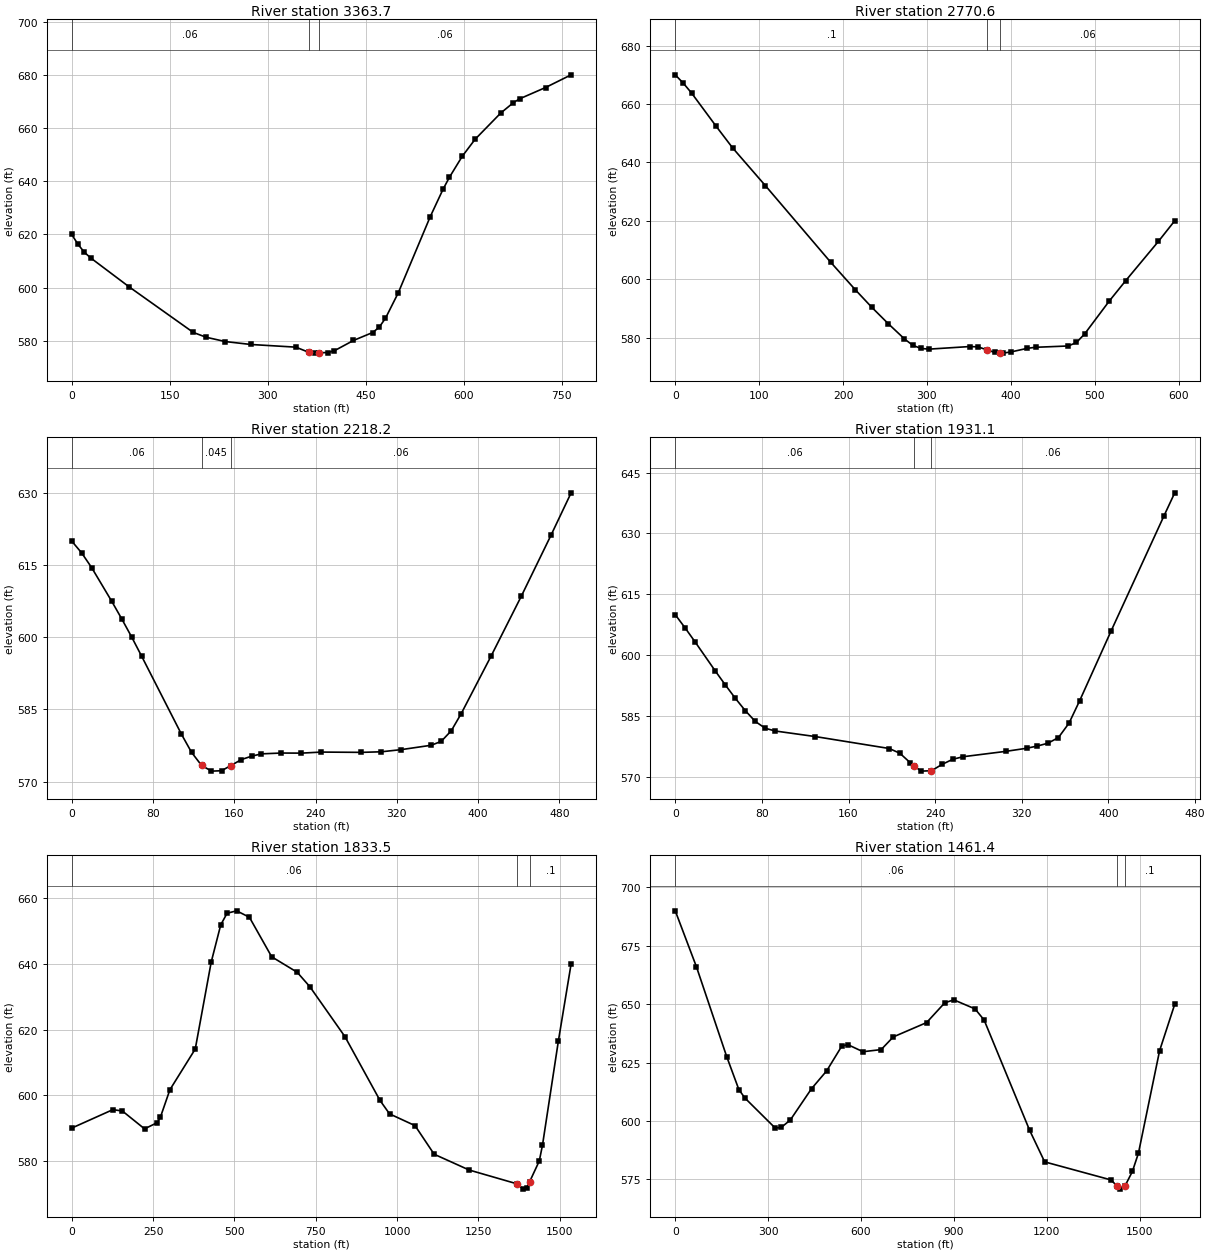
Type RM Length L Ch R = 1 ,3363.7  ,613.2,593.1,581.1
XS GIS Cut Line= 2
     1676420.521       567745.28      1676780.21      567070.631
#Sta/Elev= 30
       0  619.99     9.8  616.22    19.6  613.22    29.4  611.08    88.2  600.21
   186.2   583.1   205.8   581.3   235.2  579.67   274.4  578.57   343.1  577.57
   363.2  575.61   372.5  575.32   378.2  575.45   392.1  575.55   401.9  576.19
   431.3  580.08   460.7  583.07   470.5     585   480.3  588.41   499.9  597.99
   548.9  626.67   568.5  636.98   578.3   641.5   597.9  649.37   617.5  655.75
   656.7  665.61   676.3  669.56   686.1  671.02   725.3  675.22   764.5     680
#Mann= 3 , 0 , 0
       0     .06       0   363.2    .045       0   378.2     .06       0
Bank Sta=363.2,378.2
XS Rating Curve= 0 ,0
Exp/Cntr=0.3,0.1

Type RM Length L Ch R = 1 ,2770.6  ,551.7,552.3,552.1
XS GIS Cut Line= 2
     1677221.655      567834.476     1677031.557      567270.363
#Sta/Elev= 30
       0     670     9.8  667.07    19.5  663.74    48.8  652.35    68.3  644.99
   107.4  632.04   185.4  605.74   214.7  596.33   234.2  590.36   253.7  584.78
   273.2  579.51     283  577.35   292.8  576.25   302.5  576.02   351.3  576.91
   361.1  576.78   372.1   575.7   380.6  574.91   387.1  574.74   390.4  574.65
   400.1  575.05   419.6   576.3   429.4  576.65   468.4   577.1   478.2   578.3
   487.9  581.22   517.2  592.47   536.7  599.42   575.8  612.92   595.3     620
#Mann= 3 , 0 , 0
       0      .1       0   372.1    .045       0   387.1     .06       0
Bank Sta=372.1,387.1
XS Rating Curve= 0 ,0
Exp/Cntr=0.3,0.1

Type RM Length L Ch R = 1 ,2218.2  ,277.8,287.1,286.6
XS GIS Cut Line= 2
     1677588.052      567443.889     1677356.401      567010.375
#Sta/Elev= 30
       0  619.99     9.8  617.53    19.7  614.45    39.3  607.51    49.2  603.84
      59  600.06    68.8  596.08   108.1  579.81     118  576.06   127.8  573.36
   137.6  572.16   147.5  572.24   156.4  573.29   167.1  574.57     177  575.26
   186.8  575.75   206.4  575.92   226.1   575.9   245.8  576.12   285.1  576.06
   304.8  576.18   324.4  576.63   353.9  577.54   363.7  578.35   373.6  580.56
   383.4  584.13   412.9  596.14   442.4  608.48   471.9  621.28   491.5     630
#Mann= 3 , 0 , 0
       0     .06       0   127.8    .045       0   156.4     .06       0
Bank Sta=127.8,156.4
XS Rating Curve= 0 ,0
Exp/Cntr=0.3,0.1

Type RM Length L Ch R = 1 ,1931.1  ,75.3,97.6,103.2
XS GIS Cut Line= 3
     1677636.739      567404.075     1677677.079      567281.275
     1677685.025      566949.423
#Sta/Elev= 30
       0     610     9.2  606.71    18.5  603.23    36.9  596.17    46.2  592.72
    55.4  589.44    64.6   586.4    73.9  583.72    83.1  582.04    92.3  581.37
   129.3     580   197.6  577.06   207.4  575.89   217.1  573.53   220.6   572.8
   226.9  571.49   236.6  571.59   246.4  573.15   256.2  574.41   265.9  575.04
     305  576.35   324.5  577.12   334.3  577.67     344  578.35   353.8  579.75
   363.6  583.31   373.3  588.76   402.6  606.09   451.4  634.41   461.2     640
#Mann= 3 , 0 , 0
       0     .06       0   220.6    .045       0   236.6     .06       0
Bank Sta=220.6,236.6
XS Rating Curve= 0 ,0
Exp/Cntr=0.3,0.1

Type RM Length L Ch R = 1 ,1833.5  ,400.8,372.1,359.6
XS GIS Cut Line= 3
     1677370.768      568378.482     1677634.668      568105.398
     1677761.986      566957.487
#Sta/Elev= 30
       0     590   126.6  595.62   155.8  595.22     224  589.78   262.9  591.66
   272.6  593.29   301.9  601.68   379.8  614.07   428.7  640.47   458.1  651.85
   477.6  655.39     507  656.12   546.2  654.16   614.7  642.13     693  637.43
   732.1  633.01   839.8  617.83   947.4  598.44   976.8  594.34  1055.1  590.76
  1113.8  582.06  1221.5  577.25  1367.7  573.07  1387.9  571.44  1397.7  571.66
  1407.5  573.75  1436.8  579.99  1446.6  584.75  1495.6  616.56  1534.7  639.99
#Mann= 3 , 0 , 0
       0     .06       0  1367.7    .045       0  1407.5      .1       0
Bank Sta=1367.7,1407.5
XS Rating Curve= 0 ,0
Exp/Cntr=0.3,0.1

Type RM Length L Ch R = 1 ,1461.4  ,138,130.8,123.3
XS GIS Cut Line= 3
     1678199.495      568535.199     1678151.149      567284.335
     1678055.364      566935.905
#Sta/Elev= 30
       0  690.01    68.5  666.02   166.2  627.57   205.4  613.49   224.9  609.86
   322.7  597.01   342.3  597.26   371.6  600.44   440.1  613.85     489  621.48
   537.9   632.1   557.4  632.71   606.3  629.68     665  630.59   704.1  636.01
   811.7  642.15   870.4  650.62   899.7  651.89   968.2  648.02   997.5  643.26
  1144.2  596.14  1193.1  582.51  1408.1  574.75  1427.6  571.98  1437.4  570.84
  1452.1  572.08  1476.4   578.4    1496  586.25  1564.3  630.12  1613.2     650
#Mann= 3 , 0 , 0
       0     .06       0  1427.6    .045       0  1452.1      .1       0
Bank Sta=1427.6,1452.1
XS Rating Curve= 0 ,0
Exp/Cntr=0.3,0.1

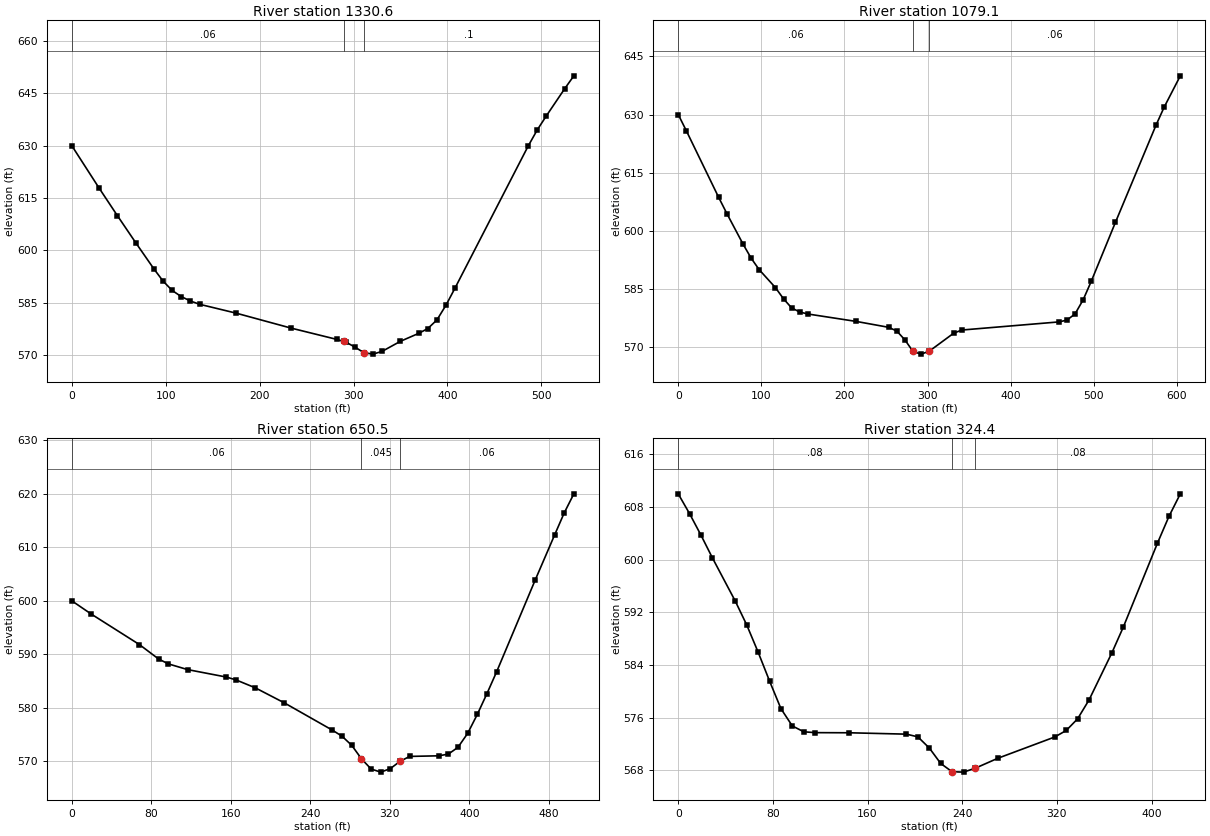
Type RM Length L Ch R = 1 ,1330.6  ,252,251.5,248.5
XS GIS Cut Line= 2
     1678393.369      567342.807      1678096.45      566898.251
#Sta/Elev= 30
       0     630    29.2   617.8    48.6  609.93      68  602.23    87.5  594.67
    97.2   591.2   106.9  588.51   116.6  586.75   126.4  585.48   136.1  584.55
     175  582.01   233.3  577.74   281.9  574.51   289.4  573.92   291.6  573.75
   301.3  572.32     311  570.69   320.8  570.27   330.5  571.07   349.9  573.94
   369.4  576.22   379.1   577.6   388.8  580.06   398.5  584.31   408.2  589.26
     486   629.9   495.7  634.54   505.4  638.56   524.9  646.33   534.6     650
#Mann= 3 , 0 , 0
       0     .06       0   289.4    .045       0     311      .1       0
Bank Sta=289.4,311
XS Rating Curve= 0 ,0
Exp/Cntr=0.3,0.1

Type RM Length L Ch R = 1 ,1079.1  ,413.1,428.5,441.4
XS GIS Cut Line= 2
     1678579.418      567223.738     1678237.171      566725.872
#Sta/Elev= 30
       0     630     9.7  625.83    48.7  608.58    58.5  604.43      78  596.53
    87.7  592.91    97.4  589.93   116.9  585.31   126.7   582.4   136.4  580.06
   146.2  578.99   155.9  578.48   214.4  576.55   253.4  575.03   263.1  574.06
   272.8  571.78   282.6  568.79   292.3  568.11   302.1  568.87   331.3  573.49
   341.1  574.33     458  576.43   467.7  576.89   477.5  578.49   487.2  582.11
     497   586.9   526.2  602.19   574.9  627.22   584.7  631.88   604.2     640
#Mann= 3 , 0 , 0
       0     .06       0   282.6    .045       0   302.1     .06       0
Bank Sta=282.6,302.1
XS Rating Curve= 0 ,0
Exp/Cntr=0.3,0.1

Type RM Length L Ch R = 1 ,650.5   ,352.2,326.2,297.9
XS GIS Cut Line= 2
     1678769.596      567095.346     1678698.802      566595.093
#Sta/Elev= 30
       0     600    19.4  597.54      68  591.82    87.4  589.11    97.2   588.2
   116.6  587.13   155.5  585.74   165.2  585.21   184.6  583.73   213.8  580.92
   262.3   575.8     272  574.67   281.8  572.95   291.5  570.45   301.2  568.54
   310.9  567.96   320.6  568.62   330.4     570   340.1   570.9   369.2  571.01
   378.9  571.33   388.6   572.6   398.4  575.22   408.1  578.77   417.8  582.66
   427.5  586.72   466.4  603.92   485.8  612.29   495.5  616.43   505.2     620
#Mann= 3 , 0 , 0
       0     .06       0   291.5    .045       0   330.4     .06       0
Bank Sta=291.5,330.4
XS Rating Curve= 0 ,0
Exp/Cntr=0.3,0.1

Type RM Length L Ch R = 1 ,324.4   ,308.6,324.4,339.7
XS GIS Cut Line= 2
     1679222.351      566733.398     1678821.466      566594.333
#Sta/Elev= 30
       0     610     9.6  606.99    19.3   603.7    28.9  600.27    48.2  593.71
    57.9  590.08    67.5  585.96    77.2  581.55    86.8  577.36    96.4  574.74
   106.1  573.85   115.7  573.72   144.6   573.7   192.9  573.49   202.5  573.08
   212.2  571.38   221.8  569.04   231.4  567.78   241.1  567.72   251.2  568.33
     270  569.82   318.2  573.06   327.9  574.05   337.5  575.82   347.2   578.7
   366.5  585.86   376.1  589.75     405  602.52   414.7  606.58   424.3  610.01
#Mann= 3 , 0 , 0
       0     .08       0   231.4    .045       0   251.2     .08       0
Bank Sta=231.4,251.2
XS Rating Curve= 0 ,0
Exp/Cntr=0.3,0.1

Chan Stop Cuts=-1
Use User Specified Reach Order=0
Composite Channel Slope=5